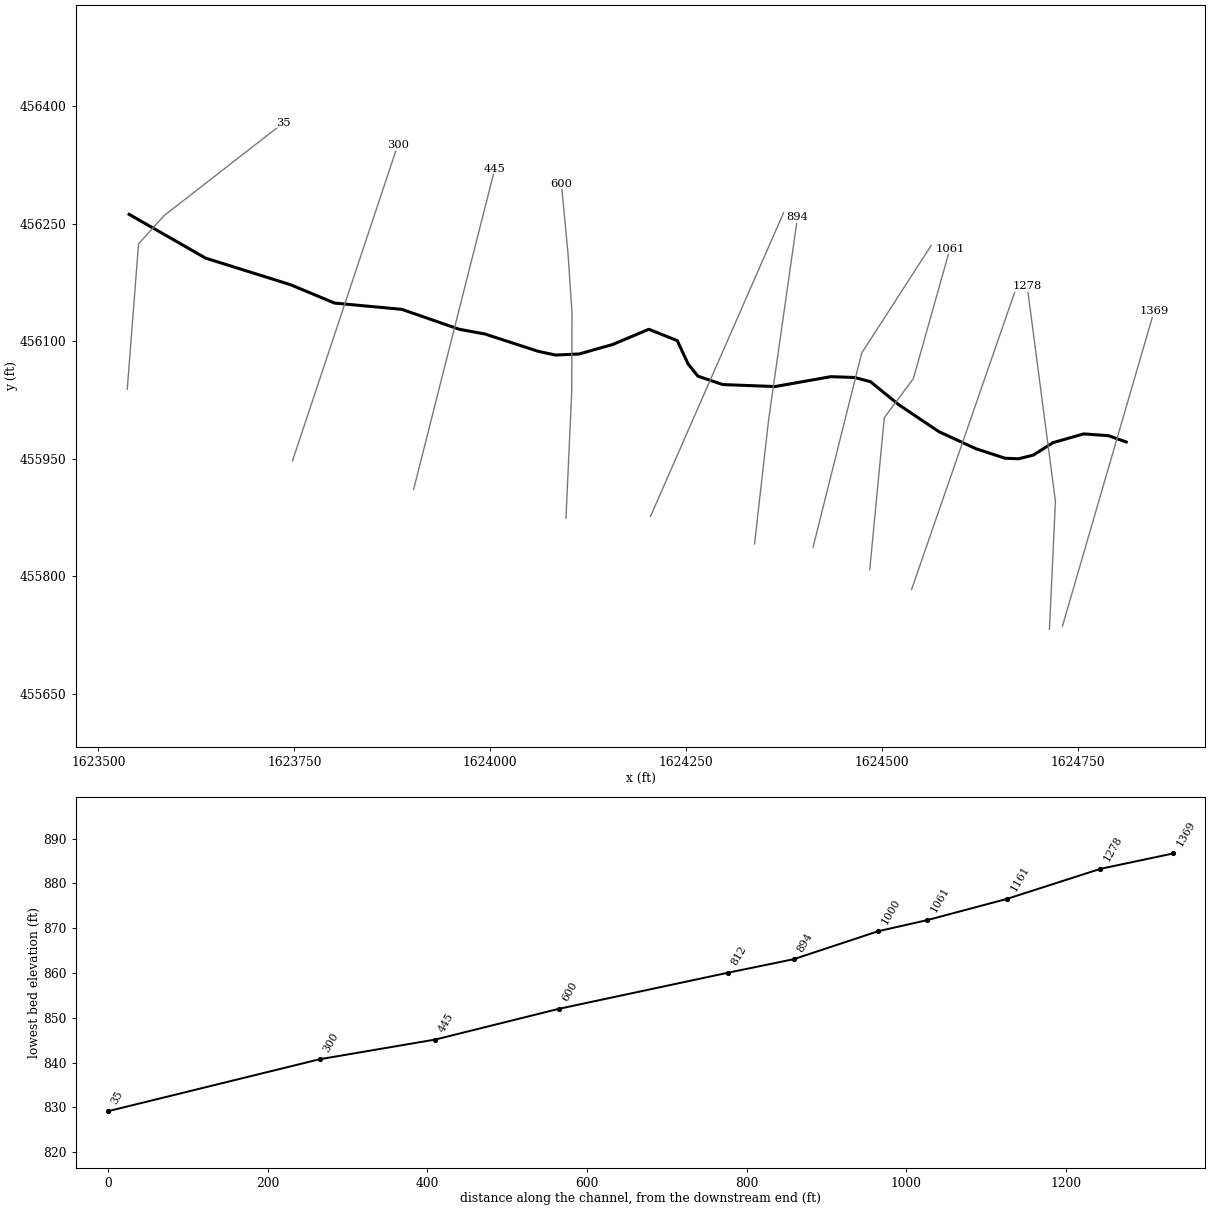
--- WhtstneCkT1.prj (project) ---

Proj Title=WhtstneCkT1
Current Plan=p01
Default Exp/Contr=0.3,0.1
English Units
Geom File=g01
Flow File=f01
Plan File=p01
Y Axis Title=Elevation
X Axis Title(PF)=Main Channel Distance
X Axis Title(XS)=Station
BEGIN DESCRIPTION:
---------- MODELED AS PART OF WVEM CTP PROGRAM, 2025----------
Stream Name: Whetstone Creek Tributary 1
Flood Zone: AFH
Marshall County, WV
HEC-RAS Version: RAS 6.6
Vertical Datum: NAVD88
Projection: NAD 1983 StatePlane West Virginia N FIPS 4701 (US Feet)
Terrain: 1-meter West Virginia FEMA R3 South Central (collected 2018-2019)
Land Use: 2024 NLCD
Hydrologic Method:
Duda et al., "Estimation of magnitude and frequency of floods for rural, unregulated streams in and near Virginia and West Virginia." September 8, 2025.
Additional Model Notes:
None
END DESCRIPTION:
DSS Export Rating Curves= 0
DSS Export Rating Curve Sorted= 0
DSS Export Volume Flow Curves= 0
DXF OffsetX= 0
DXF OffsetY= 0
DXF ScaleX= 1
DXF ScaleY= 10

--- WhtstneCkT1.p01 (plan) ---

Plan Title=Floodplain
Program Version=6.60
Short Identifier=Floodplain
Geom File=g01
Flow File=f01
Subcritical Flow
K Sum by GR= 0
Std Step Tol= 0.01
Critical Tol= 0.01
Num of Std Step Trials= 20
Max Error Tol= 0.3
Flow Tol Ratio= 0.001
Split Flow NTrial= 30
Split Flow Tol= 0.02
Split Flow Ratio= 0.02
Log Output Level= 0
Friction Slope Method= 1
Unsteady Friction Slope Method= 2
Unsteady Bridges Friction Slope Method= 1
Parabolic Critical Depth
Global Vel Dist= 0 , 0 , 0
Global Log Level= 0
CheckData=True
Encroach Param=-1 ,0,0, 0
Flow Ratio Tolerance=0.1
Flow Ratio Min Ratio=0.5
Flow Ratio Max Ratio=4
Flow Ratio Max Iterations= 10
Computation Interval=1MIN
Output Interval=1HOUR
Instantaneous Interval=1HOUR
Mapping Interval=1HOUR
Computation Time Step Use Courant=        0
Computation Time Step Use Time Series=    0
Computation Time Step Count To Double=0
Computation Time Step Max Doubling=0
Computation Time Step Max Halving=0
Computation Time Step Residence Courant=0
Run HTab= 0
Run UNet= 0
Run Sediment= 0
Run PostProcess= 0
Run WQNet= 0
Run RASMapper=-1
UNET Theta= 1
UNET Theta Warmup= 1
UNET ZTol= 0.02
UNET ZSATol= 0.02
UNET MxIter= 20
UNET Max Iter WO Improvement= 0
UNET MaxInSteps= 0
UNET DtIC= 0
UNET DtMin= 0
UNET MaxCRTS= 20
UNET WFStab= 2
UNET SFStab= 1
UNET WFX= 1
UNET SFX= 1
UNET Gravity=32.17405
UNET 1D Methodology=Finite Difference
UNET DSS MLevel= 4
UNET Pardiso=0
UNET DZMax Abort= 100
UNET Use Existing IB Tables=-1
UNET Froude Reduction=False
UNET Froude Limit= 0.8
UNET Froude Power= 4
UNET D1 Cores= 0
UNET WindReference=Eulerian
UNET WindDragFormulation=Hsu (1988)
UNET D2 Coriolis=0
UNET D2 Cores= 0
UNET D2 Theta= 1
UNET D2 Theta Warmup= 1
UNET D2 Z Tol= 0.01
UNET D2 Volume Tol= 0.01
UNET D2 Max Iterations= 20
UNET D2 Advanced Convergence=0
UNET D2 WS Max Tol=0.15
UNET D2 WS RMS Tol=0.002
UNET D2 WS Stall Tol=1
UNET D2 Equation= 0
UNET D2 RampUpFraction=0.1
UNET D2 TimeSlices= 1
UNET D2 Turbulence Formulation=None
UNET D2 Eddy Viscosity=0.3
UNET D2 Transverse Eddy Viscosity=0.1
UNET D2 Smagorinsky Mixing=0.05
UNET D2 BCVolumeCheck=0
UNET D2 Cores=0
UNET D2 SolverType=PARDISO (Direct)
UNET D2 Minimum Iterations= 3
UNET D2 Maximum Iterations= 30
UNET D2 Restart Number= 10
UNET D2 Relaxation Coeff=1.3
UNET D2 SOR Precondition Iterations= 10
UNET D2 ILUT Maximum Fill= 8
UNET D2 ILUT Tolerance=1E-08
UNET D2 Convergence Tolerance=0.00001
PS Theta= 1
PS WS Tol= 0.01
PS Volume Tol= 0.01
PS Max Iterations= 20
PS Equation= 0
PS Advance Time Step=-1
PS Target Courant=0.9
PS Time Slices= 1
PS Iterate With 2D=0
PS Project Initial WSE from DS=-1
PS Ramp Up Initial WSE from US=-1
PS Cores=0
UNET D1D2 MaxIter= 0
UNET D1D2 ZTol=0.01
UNET D1D2 QTol=0.1
UNET D1D2 MinQTol=1
Write IC File= 0
Write IC File at Fixed DateTime=0
Write IC File at Sim End=0
Echo Input=False
Echo Parameters=False
Echo Output=False
Write Detailed= 0
HDF Write Warmup=0
HDF Write Time Slices=0
HDF Flush=0
HDF Compression= 1
HDF Chunk Size= 1
HDF Spatial Parts= 1
HDF Use Max Rows=0
HDF Fixed Rows= 1
Calibration Method= 0
Calibration Iterations= 20
Calibration Max Change=0.05
Calibration Tolerance=0.2
Calibration Maximum=1.5
Calibration Minimum=0.5
Calibration Optimization Method= 1
WQ AD Non Conservative
WQ ULTIMATE=-1
WQ Max Comp Step=1HOUR
WQ Output Interval=15MIN
WQ Output Selected Increments= 0
WQ Create Restart=0
WQ Fixed Restart=0
WQ System Summary=0
WQ Write To DSS=0
Sorting and Armoring Iterations= 10
XS Update Threshold= 0.02
Bed Roughness Predictor= 0
Processes Affected by Predictor=Sediment Only
Hydraulics Update Threshold= 0.02
Energy Slope Method= 1
Volume Change Method= 1
Sediment Retention Method= 0
Sediment TS Multiplier= 1
Warm Up Method= 0
XS Weighting Method= 0
Number of US Weighted Cross Sections= 1
Number of DS Weighted Cross Sections= 1
Upstream XS Weight=0
Main XS Weight=1
Downstream XS Weight=0
Number of DS XS's Weighted with US Boundary= 1
Upstream Boundary Weight= 1
Weight of XSs Associated with US Boundary= 0
Number of US XS's Weighted with DS Boundary= 1
Downstream Boundary Weight= 0.5
Weight of XSs Associated with DS Boundary= 0.5
Percentile Method= 0
Sediment Output Level= 3
Mass or Volume Output= 0
Output Increment Type= 1
Profile and TS Output Increment= 1
Transport Output Increment 1
XS Output Flag= 0
XS Output Increment= 10
Read HDF5 Sediment Hotstart= 0
Sediment Hotstart Type= 0
Write Gradation File= 0
Read Gradation Hotstart= 0
Write HDF5 File= 1
Write Binary Output= 1
Write DSS Sediment File= 0
DSS Sediment Output Type= 1
SV Curve= 0
Specific Gage Flag= 0
Subcell Erosion Methods= 0
Subcell Deposition Methods= 0
Advection Scheme= 1
Matrix Solver= 0
Implicit Weighting Factor= 1
Maximum Outer Loop Convergence Iterations= 5
Convergence Maximum Absolute= 0.001
Convergence RMSE= 0.0001
Grain Fractions Max Abs Error= 0.001
Max Subgrid Regions= 1
Max Subgrid Length Scale= 3.402823E+38
Initial Layer Thickness= 3
Min Layer Thickness= 0.1
Max Layer Thickness= 6
Number of Layers= 5

--- WhtstneCkT1.f01 (steady flow) ---

Flow Title=Flow
Program Version=6.60
Number of Profiles= 1
Profile Names=P100yr
River Rch & RM=WhtstneCkT1,Main            ,1369
     689
Boundary for River Rch & Prof#=WhtstneCkT1,Main            , 1
Up Type= 0
Dn Type= 3
Dn Slope=0.093
DSS Import GetInterval= 0
DSS Import GetPeak= 0
DSS Import FillOption= 0

--- WhtstneCkT1.g01 (geometry) ---

Geom Title=Geometry
Program Version=6.60

River Reach=WhtstneCkT1     ,Main
Reach XY= 30
1624811.57124673455971.2361871121624788.80335812455979.312479008
1624757.22066523455981.5683856431624717.83579839455970.318008339
 1624693.0969052455954.5589150461624674.08047309 455949.81726152
1624656.89263487455950.5198852361624619.61119306455962.704842225
1624572.44199605455984.4751398861624521.28625762456018.810377405
1624485.20488999456048.2021200561624465.00080938456053.563808534
1624434.56333481456054.6239497211624363.39465798456041.991151998
1624296.62213232456044.5321194081624264.90939323 456055.25848704
1624252.38530125456070.9005185661624238.63032772 456100.58350347
1624202.34627956456115.096925899 1624156.3867258456095.745586649
1624113.36526405 456083.551716481624083.34135926456082.204207516
1624061.51553294456086.821209236  1623993.099962456109.066762978
1623960.45371872456115.0969258991623886.90892244 456140.54632016
1623801.28452691456148.5211413131623745.16937239456171.941956565
1623636.85357125 456205.817410981623539.07595256456261.789217815

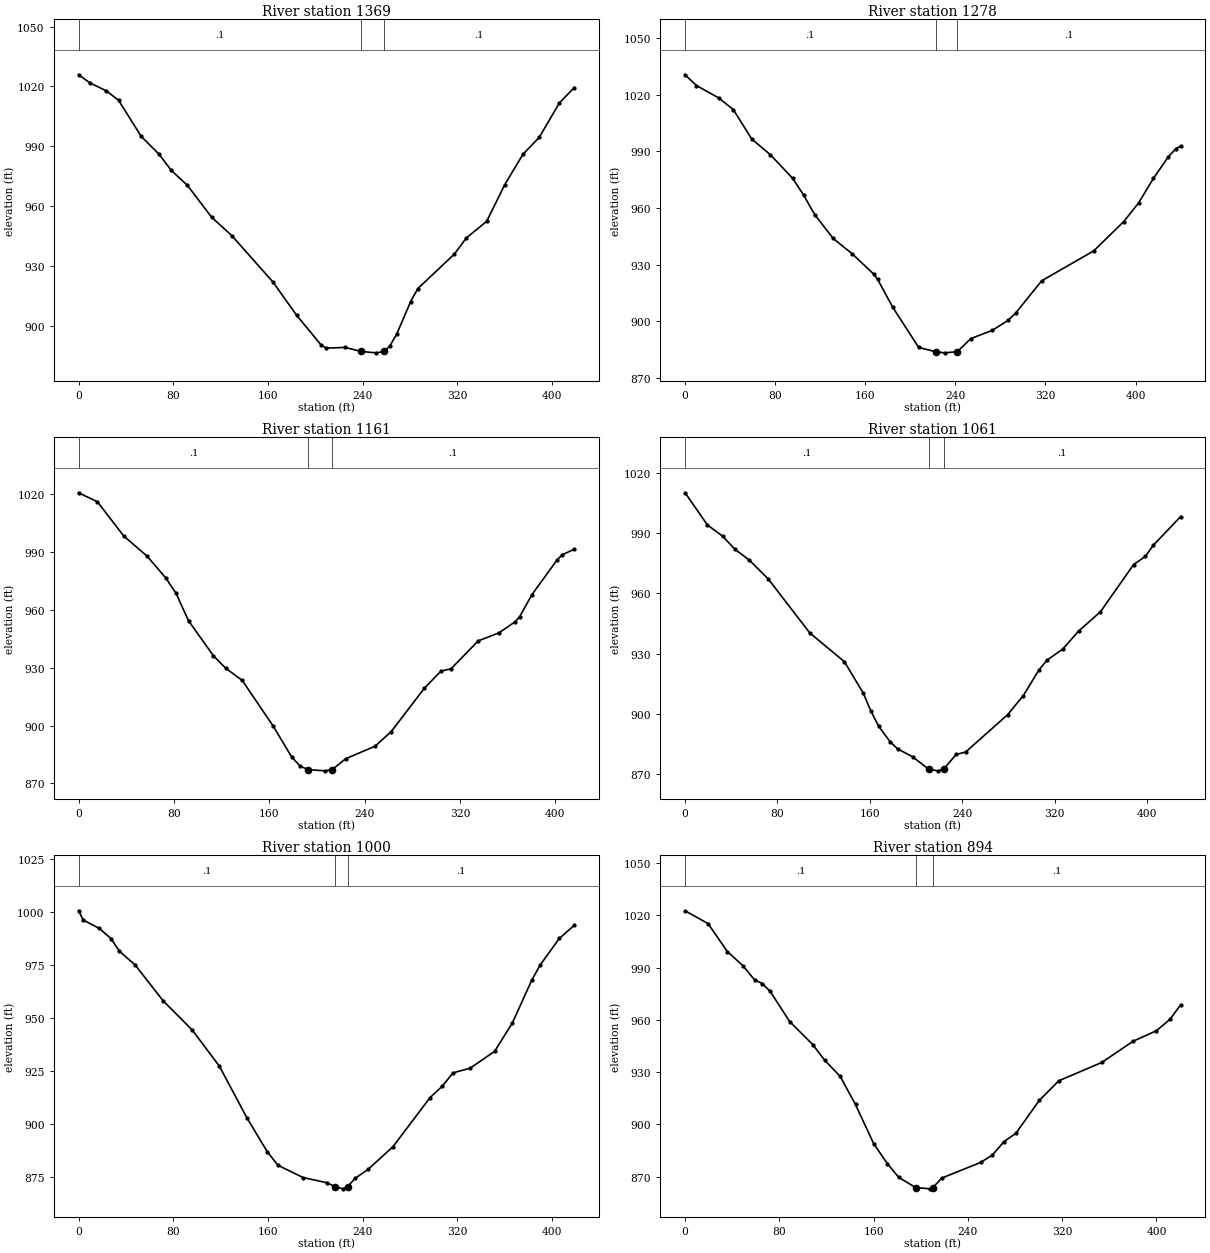
Type RM Length L Ch R = 1 ,1369    ,87,91.4,94.7
XS GIS Cut Line= 2
1624730.12193491455736.1758750381624847.09487153456138.154300082
#Sta/Elev= 30
       0 1025.84     9.8 1021.69    23.5 1017.77    33.8 1013.03    52.9  994.98
    67.9  986.12    78.2  978.04    91.8  970.58   112.3   954.6   129.4  945.34
   164.1  922.18   184.1  905.54   204.6   890.8   209.1  889.05   225.1  889.39
   238.8  887.37   251.4  886.69  258.21  887.38   262.7  889.92   268.7  896.05
   280.5  912.37   286.6  918.88   317.4  936.09   327.6  944.22   344.7  952.48
   359.9  970.73   375.4  986.06   389.1  994.48   406.2 1011.78418.6518 1019.41
#Mann= 3 ,-1,0
       0      .1       0   238.8    .045       0  258.21      .1       0
Bank Sta=238.8,258.21
XS Rating Curve= 0 ,0
Exp/Cntr(USF)=0,0
Exp/Cntr=0.3,0.1

Type RM Length L Ch R = 1 ,1278    ,120.4,117,112.2
XS GIS Cut Line= 3
1624713.55230327455732.377679638 1624721.2204237455895.417800763
1624685.20423776 456169.81728892
#Sta/Elev= 30
       0 1030.58    10.1 1024.88    29.7 1018.38    42.8 1012.15    59.2  996.51
    75.7  988.24    95.4  975.77   105.2  966.88   115.1  956.46   131.5  943.84
   148.1  935.88   167.6  924.89     171  922.16   184.2  907.56   207.4   886.1
  222.36883.8666   230.5  883.25  241.68883.8658   253.7   890.8   272.9   895.2
   286.8   900.5   293.4  904.24   316.6  921.42   362.9   937.3   389.4  952.75
   402.6  962.61   415.8  975.67   429.1  987.14   435.7  991.37     440  992.76
#Mann= 3 ,-1,0
       0      .1       0  222.36    .045       0  241.68      .1       0
Bank Sta=222.36,241.68
XS Rating Curve= 0 ,0
Exp/Cntr(USF)=0,0
Exp/Cntr=0.3,0.1

Type RM Length L Ch R = 1 ,1161    ,101.9,99.9,96.9
XS GIS Cut Line= 2
1624537.66664973455783.1994328241624673.92932675456175.994191952
#Sta/Elev= 30
       0 1020.64    15.8 1015.97    37.8  998.27    57.5  987.77    73.2  976.42
    81.8  968.47    92.2  954.34     113  936.26   123.4  929.72   137.3  923.41
   163.3  899.67   178.7  883.81   185.9  878.95  192.69877.1712   206.8  876.55
  212.71 877.173   224.1  882.84   248.7  889.29   262.3   896.9   290.1  919.36
     304  928.23   312.5  929.43   335.3   943.9   352.6  948.03   366.5   953.9
     370  956.39   380.4   967.9   401.2  985.62   405.6  988.47   415.8  991.35
#Mann= 3 ,-1,0
       0      .1       0  192.69    .045       0  212.71      .1       0
Bank Sta=192.69,212.71
XS Rating Curve= 0 ,0
Exp/Cntr(USF)=0,0
Exp/Cntr=0.3,0.1

Type RM Length L Ch R = 1 ,1061    ,58.6,61.5,63
XS GIS Cut Line= 4
1624484.25592423455808.407230043 1624502.8081197456002.245686094
1624539.91251062456052.1446945831624586.61286472   456217.834992
#Sta/Elev= 30
       0 1009.93    19.3  993.97    32.5  988.36      43  981.94    55.6  976.48
      72  967.12     108  940.29     138     926   154.4  910.27     161  901.34
   167.6  893.98   177.5  886.27   184.1   882.7     197  878.79  210.83 872.668
   218.9  871.81  223.92872.6662   234.7  879.95   242.9  881.14   279.3  899.71
   292.9  909.22   306.5  922.01   313.4  926.79     327  932.27   340.7  941.19
   359.7  950.85   388.4  974.29   398.6  978.36   405.4  983.84   429.1  998.11
#Mann= 3 ,-1,0
       0      .1       0  210.83    .045       0  223.92      .1       0
Bank Sta=210.83,223.92
XS Rating Curve= 0 ,0
Exp/Cntr(USF)=0,0
Exp/Cntr=0.3,0.1

Type RM Length L Ch R = 1 ,1000    ,105.3,106,105.5
XS GIS Cut Line= 3
1624411.92882511455837.0155134791624473.95521185456084.654696645
1624562.61615397456222.054815173
#Sta/Elev= 30
       0  1000.6     3.9  996.22    17.4   992.3    27.5  987.42    34.3   981.6
    47.8  974.99    71.5  958.04      96  944.32   118.9  927.28   142.5  902.58
   159.4  886.89   168.4  880.47   189.7  874.66   210.2  872.16  216.52870.3604
   223.7  869.33  227.26870.3601   233.8  874.34   244.5  878.46   265.7  889.25
   296.9  912.34   307.2  917.72   316.4  924.08   330.9  926.29   351.6  934.27
   366.5  947.58   383.1  968.01   390.2  975.09   406.2  987.53   418.8  993.69
#Mann= 3 ,-1,0
       0      .1       0  216.52    .045       0  227.26      .1       0
Bank Sta=216.52,227.26
XS Rating Curve= 0 ,0
Exp/Cntr(USF)=0,0
Exp/Cntr=0.3,0.1

Type RM Length L Ch R = 1 ,894     ,83.7,81.9,79.6
XS GIS Cut Line= 3
1624337.22993919455841.2001244841624355.03028687455998.407300826
1624392.05415049456258.058645502
#Sta/Elev= 30
       0 1022.57    19.4 1015.26    35.9  999.17    49.1  991.04      59   982.9
    65.6  980.84    72.2  976.35    88.7  959.06   108.5   945.7   118.4  936.88
   131.6  927.56   144.6  911.46   160.1  888.88   171.7   877.5   181.2   869.7
  195.59863.8322   207.8  863.08  210.33863.8314   217.7  869.23   250.8  878.21
   260.8  882.52   270.7  890.23   280.7  894.95   300.5  913.75   317.1  925.04
   353.6  935.57   380.1  947.72     400  953.79   411.4  960.26   420.5  968.65
#Mann= 3 ,-1,0
       0      .1       0  195.59    .045       0  210.33      .1       0
Bank Sta=195.59,210.33
XS Rating Curve= 0 ,0
Exp/Cntr(USF)=0,0
Exp/Cntr=0.3,0.1

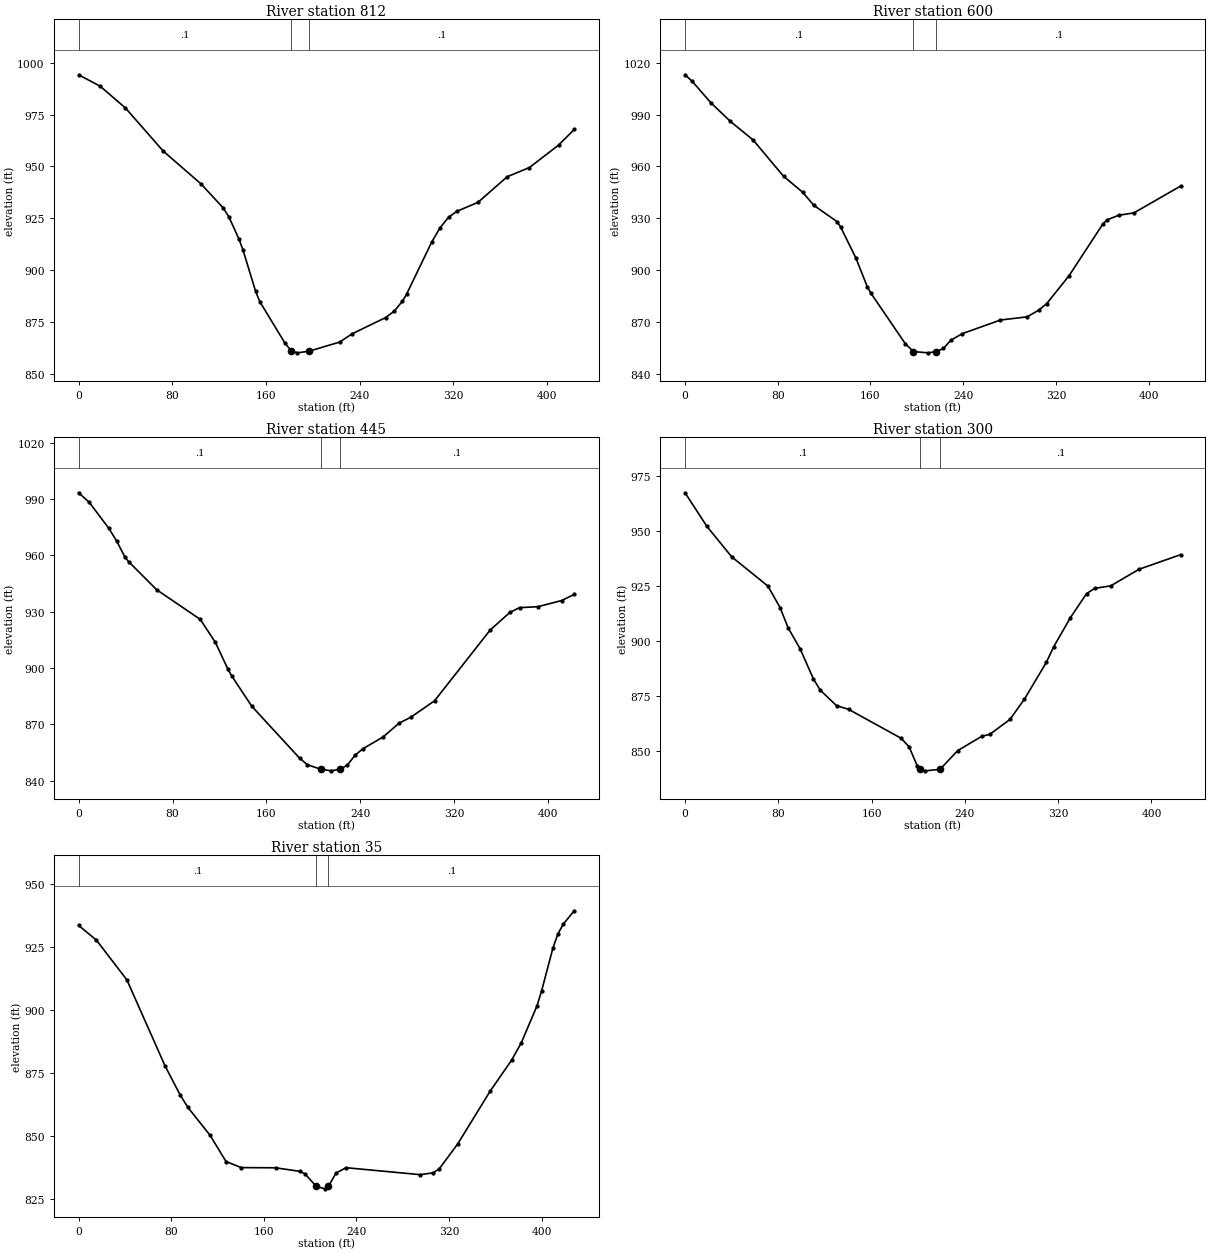
Type RM Length L Ch R = 1 ,812     ,206,212.2,213.5
XS GIS Cut Line= 2
1624204.46410135455876.3391308221624374.31264948456263.824123663
#Sta/Elev= 30
       0  994.16    18.5  988.61      40  978.12    72.2  957.38   104.4  941.58
   123.3  930.05   128.3  925.62   136.7  915.15   140.3  909.73     151   889.9
   154.6  884.82   176.1  864.82   181.7860.8755   186.8  860.08  196.71860.8771
   222.9  865.28   233.4  869.23   262.1   877.1   269.2  880.06   276.4  884.94
     280   888.4   301.5  913.58   308.6  920.42   315.8  925.45   322.9  928.33
   340.9  932.63   365.9     945   384.8  949.42   409.7  960.24   423.1  967.78
#Mann= 3 ,-1,0
       0      .1       0   181.7    .045       0  196.71      .1       0
Bank Sta=181.7,196.71
XS Rating Curve= 0 ,0
Exp/Cntr(USF)=0,0
Exp/Cntr=0.3,0.1

Type RM Length L Ch R = 1 ,600     ,157.6,154.7,152.7
XS GIS Cut Line= 6
1624096.58074309455873.9799540941624100.55383226455961.389884248
1624103.95933726456036.3126346771624104.24870676456136.402657583
1624099.17817885456211.7105778461624090.72576793456300.879690841
#Sta/Elev= 30
       0 1013.13     6.2 1009.33    22.3  996.91      39   986.2    58.7  975.37
      85  954.32   101.4  945.12   111.2  937.44     131  928.11   134.2  924.97
   147.4  906.97   157.2  890.37   160.5  886.44     190  857.35  197.06852.7462
   209.7  852.01  216.81852.7465   222.9  854.54   229.4  859.37   239.3  863.15
   272.1  871.02   295.1  872.86     305  876.67   311.9  880.41   331.3  896.66
   360.6  926.77   364.2  929.07   374.1  931.71   387.3  933.12   427.6  948.66
#Mann= 3 ,-1,0
       0      .1       0  197.06    .045       0  216.81      .1       0
Bank Sta=197.06,216.81
XS Rating Curve= 0 ,0
Exp/Cntr(USF)=0,0
Exp/Cntr=0.3,0.1

Type RM Length L Ch R = 1 ,445     ,145.6,145,144.3
XS GIS Cut Line= 2
1623902.19126147455910.8845982371624005.82766371456320.248387108
#Sta/Elev= 30
       0  993.27     8.9  988.27    25.8   974.3    32.6  967.36    39.3  959.18
    42.7  956.52    66.4  941.67   103.6  925.84   116.4  913.74   127.3  899.23
   130.7  895.45   147.6  879.52   188.3   851.9     195  848.38  206.14846.0627
   215.3  845.16  222.88846.0618   228.9  848.16   235.6  853.51   242.4  856.98
   259.3  863.14     273  870.54     283  873.69   303.3  882.48   350.7  920.19
   367.6  929.61   375.7  932.08   391.3  932.59   411.6  935.87   422.3  939.14
#Mann= 3 ,-1,0
       0      .1       0  206.14    .045       0  222.88      .1       0
Bank Sta=206.14,222.88
XS Rating Curve= 0 ,0
Exp/Cntr(USF)=0,0
Exp/Cntr=0.3,0.1

Type RM Length L Ch R = 1 ,300     ,267.8,265.2,263.3
XS GIS Cut Line= 6
1623747.54338342455947.1556607481623775.21360368456030.165665343
1623798.93074784456101.3167697491623830.55338801456196.185346425
1623854.27053218456267.3364508451623881.94042434456350.346127346
#Sta/Elev= 30
       0  967.32    18.6  952.13      40  938.18    71.1  924.84    81.5  915.06
    88.4  905.87    98.8  896.21   110.1  882.57   116.1  877.39   129.9  870.44
   140.3  868.75   185.3  855.58   192.2  851.67   199.1  843.03  201.87 841.435
     206  840.76  218.68841.4361   233.9     850   254.4  856.45   261.3  857.36
   278.6  864.14     291  873.35   309.8   890.1   316.2  897.31   330.5   910.5
   344.3  921.41   351.3  923.81   365.1  924.97   389.3   932.5     425  939.15
#Mann= 3 ,-1,0
       0      .1       0  201.87    .045       0  218.68      .1       0
Bank Sta=201.87,218.68
XS Rating Curve= 0 ,0
Exp/Cntr(USF)=0,0
Exp/Cntr=0.3,0.1

Type RM Length L Ch R = 1 ,35      ,,,
XS GIS Cut Line= 4
1623536.71580805456038.643690048 1623551.1097528456224.037698508
1623583.92794685456260.3104392931623736.50376126456378.916544084
#Sta/Elev= 30
       0  933.46    15.4  927.61    41.7  911.89    74.6  877.88    87.8  866.24
    94.4   861.4   113.5  850.38   127.3  839.97   140.5  837.57   170.1  837.49
   191.2  836.08   195.6  835.04  205.17830.1643   212.8  829.16  215.83830.1656
   222.3  835.39     231  837.53   295.1  834.77   306.4  835.53   311.7  837.19
   327.5  846.98   355.5  867.87     374   880.1   382.3  886.91   395.9  901.56
   399.9  907.53   409.6  924.33     414  930.13   418.6  933.96   428.1  939.26
#Mann= 3 ,-1,0
       0      .1       0  205.17    .045       0  215.83      .1       0
Bank Sta=205.17,215.83
XS Rating Curve= 0 ,0
Exp/Cntr(USF)=0,0
Exp/Cntr=0.3,0.1
LCMann Table=0

Chan Stop Cuts=-1
Use User Specified Reach Order=0
Composite Channel Slope=5